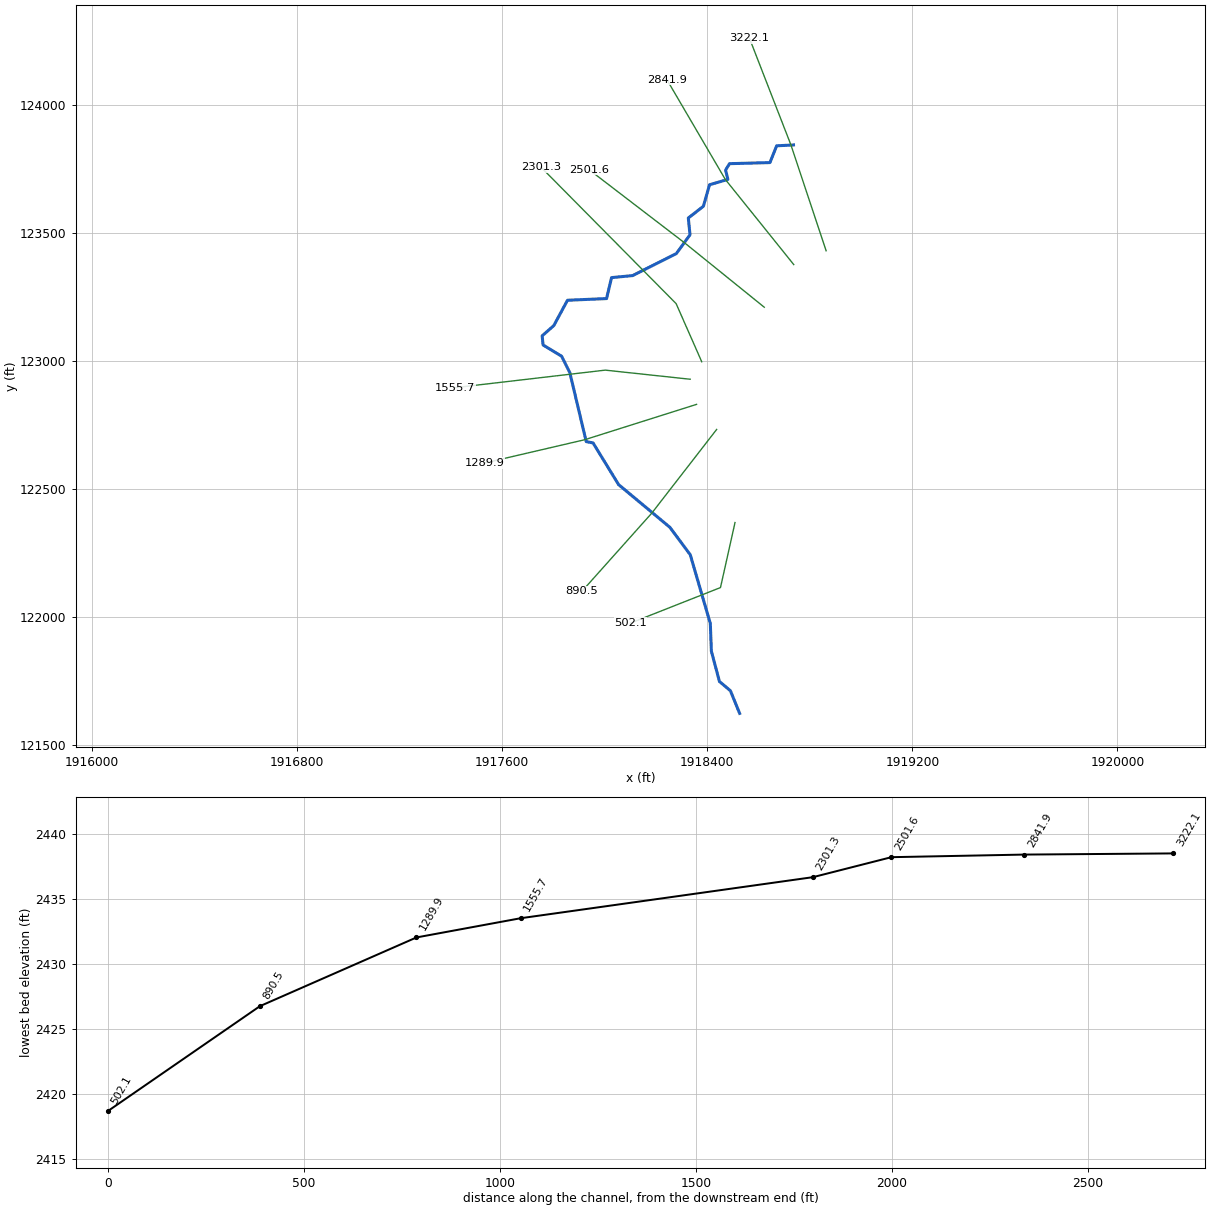
--- MllCrk2.prj (project) ---

Proj Title=MllCrk2
Current Plan=p01
Default Exp/Contr=0,0
English Units
Geom File=g01
Flow File=f01
Plan File=p01
BEGIN DESCRIPTION:
END DESCRIPTION:
DSS Export Rating Curves= 0
DSS Export Rating Curve Sorted= 0
DSS Export Volume Flow Curves= 0
DXF OffsetX= 0
DXF OffsetY= 0
DXF ScaleX= 0
DXF ScaleY= 0

--- MllCrk2.p01 (plan) ---

Plan Title=Floodplain
Program Version=4.00
Geom File=g01
Flow File=f01
K Sum by GR=0
Std Step Tol=0.01
Critical Tol=0.01
Num of Std Step Trials=20
Max Error Tol=0.3
Flow Tol Ratio=0.001
Split Flow NTrial=30
Split Flow Tol=0.02
Split Flow Ratio=0.02
Log Output Level=0
Friction Slope Method=1
Unsteady Friction Slope Method=2
Unsteady Bridges Friction Slope Method=1
Global Log Level=0
CheckData=False
Run HTab=0
Run UNet=0
Run PostProcess=0
UNET Theta=0
UNET Theta Warmup=0
UNET ZTol=0
UNET ZSATol=0
UNET MxIter=0
UNET MaxInSteps=0
UNET DtIC=0
UNET DtMin=0
UNET MaxCRTS=0
UNET WFStab=0
UNET SFStab=0
UNET WFX=0
UNET SFX=0
UNET DSS MLevel=0
UNET DZMax Abort=0
UNET Convert EG Bridges=0
UNET Use Existing IB Tables=0
UNET Froude Limit=0
UNET Froude Power=0
Write IC File=0
Echo Input=False
Echo Output=False
Write Detailed=0

--- MllCrk2.f01 (steady flow) ---

Flow Title=NFF Regression Equation
Program Version=4.00
Number of Profiles=1
Profile Names=P100yr
River Rch & RM=MllCrk2,Main      ,3222.1
531.5361
River Rch & RM=MllCrk2,Main      ,502.1
549.9452
Boundary for River Rch & Prof#=MllCrk2,Main      ,1
Up Type=0
Dn Type=3
Dn Slope=0.013909

--- MllCrk2.g01 (geometry) ---

Geom Title=USGS 3m DEM
Program Version=4.10

River Reach=MllCrk2         ,Main
Reach XY= 30
     1918736.374      123845.425     1918670.758      123842.123
      1918644.49      123776.482     1918486.739      123772.242
     1918471.527      123747.322     1918480.372       123710.83
     1918408.793      123689.795     1918384.899      123605.778
     1918326.077      123559.856     1918332.642      123494.203
      1918279.19      123420.619     1918108.617      123334.681
     1918026.585      123326.869     1918007.054      123244.837
      1917854.71      123238.327     1917801.325      123139.369
     1917755.752      123099.004     1917759.521      123063.467
     1917831.695      123019.489     1917863.842      122955.228
     1917927.746      122685.725     1917954.398      122680.595
     1918054.228      122517.417     1918253.864      122350.926
     1918333.637      122243.467     1918411.876      121974.778
     1918415.952      121866.523     1918447.497      121747.996
     1918490.153      121711.916     1918526.275      121623.292

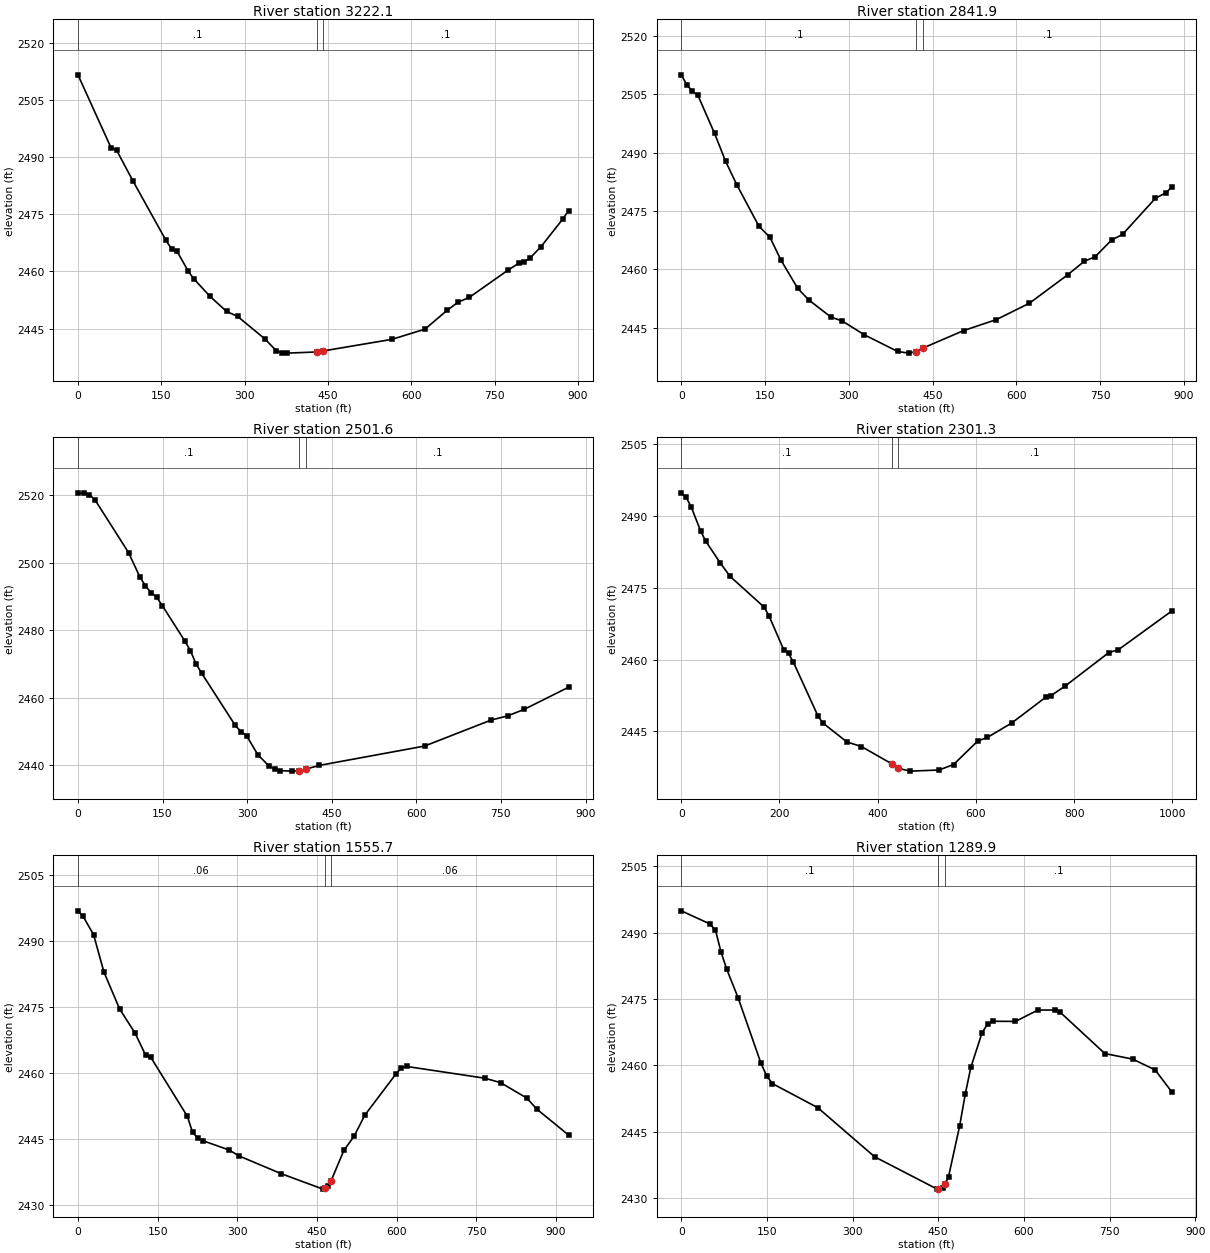
Type RM Length L Ch R = 1 ,3222.1  ,371,380.2,357
XS GIS Cut Line= 3
     1918863.707      123431.663     1918726.374      123845.412
     1918564.733      124262.232
#Sta/Elev= 30
       0 2511.71    59.4 2492.59    69.4 2491.93    99.1 2483.77   158.5 2468.16
   168.4 2465.97   178.3 2465.33   198.2 2460.15   208.1 2458.14   237.8 2453.44
   267.5 2449.49   287.3 2448.19   336.9 2442.22   356.7 2439.19   366.6 2438.54
   376.5 2438.53   429.9 2438.84   441.9 2439.12   565.1 2442.15   624.7 2444.84
   664.4 2449.78   684.3 2451.93   704.2 2453.17   773.7 2460.31   793.6 2462.19
   803.5 2462.55   813.5  2463.5   833.3 2466.49   873.1 2473.87     883    2476
#Mann= 3 , 0 , 0
       0      .1       0   429.9    .045       0   441.9      .1       0
Bank Sta=429.9,441.9
XS Rating Curve= 0 ,0
Exp/Cntr=0.3,0.1

Type RM Length L Ch R = 1 ,2841.9  ,337.7,338.9,367.2
XS GIS Cut Line= 3
     1918737.354      123377.824      1918470.25      123710.824
     1918242.596      124100.533
#Sta/Elev= 30
       0 2510.04     9.9 2507.47    19.9 2505.84    29.8 2504.75    59.6 2494.95
    79.4 2487.78    99.3 2481.77     139 2471.09   158.8 2468.23   178.7 2462.29
   208.5 2455.09   228.3 2452.12     268  2447.7   287.9 2446.73   327.6 2443.16
   387.2 2438.87     407 2438.44   420.9 2438.84   432.9 2439.76   505.4 2444.24
   564.2 2447.08   623.1 2451.27   691.8  2458.6   721.2 2462.05   740.9 2463.25
   770.3 2467.54   789.9 2468.98   848.8 2478.29   868.4 2479.76   878.2 2481.26
#Mann= 3 , 0 , 0
       0      .1       0   420.9    .045       0   432.9      .1       0
Bank Sta=420.9,432.9
XS Rating Curve= 0 ,0
Exp/Cntr=0.3,0.1

Type RM Length L Ch R = 1 ,2501.6  ,201.9,200.3,198.1
XS GIS Cut Line= 3
     1918622.396      123211.054     1918312.581      123461.865
     1917938.841      123748.826
#Sta/Elev= 30
       0 2520.55      10 2520.71    19.9 2520.21    29.9 2518.72    89.7    2503
   109.6 2495.85   119.6 2493.16   129.6 2491.16   139.5 2489.79   149.5 2487.31
   189.3 2476.86   199.3 2473.96   209.3 2470.05   219.2 2467.29     279 2451.77
     289 2449.92     299 2448.73   318.9  2443.1   338.8 2439.75   348.8 2438.78
   358.8 2438.38   378.7 2438.24   392.6 2438.35   404.6 2438.86   428.1 2439.94
   614.6 2445.67   732.4 2453.36   761.8 2454.61   791.3 2456.55   869.8  2463.1
#Mann= 3 , 0 , 0
       0      .1       0   392.6    .045       0   404.6      .1       0
Bank Sta=392.6,404.6
XS Rating Curve= 0 ,0
Exp/Cntr=0.3,0.1

Type RM Length L Ch R = 1 ,2301.3  ,724.8,745.2,764.3
XS GIS Cut Line= 3
     1918378.362        122997.9     1918278.491      123225.157
     1917750.728      123759.225
#Sta/Elev= 30
       0 2494.85     9.9  2493.9    19.9 2491.98    39.7  2486.8    49.6 2484.79
    79.4 2480.19    99.3  2477.4   168.8 2470.96   178.7 2469.12   208.5 2462.09
   218.4  2461.3   228.4 2459.44   277.9 2448.32   287.8  2446.8   337.2  2442.8
   366.8 2441.84     429 2438.21     441 2437.32   465.6  2436.7   524.9 2436.93
   554.5 2438.08   603.9    2443   623.6 2443.75     673 2446.76   742.2 2452.14
   752.1 2452.42   781.7 2454.47   870.6 2461.46   890.4 2462.08   999.1 2470.17
#Mann= 3 , 0 , 0
       0      .1       0     429    .045       0     441      .1       0
Bank Sta=429,441
XS Rating Curve= 0 ,0
Exp/Cntr=0.3,0.1

Type RM Length L Ch R = 1 ,1555.7  ,266.8,265.7,268.5
XS GIS Cut Line= 3
     1918333.362      122929.533     1918001.903      122965.117
     1917415.631      122896.561
#Sta/Elev= 30
       0  2496.9     9.8 2495.62    29.4 2491.48      49 2482.94    78.4 2474.58
   107.8    2469   127.5 2464.01   137.3 2463.51   205.9 2450.14   215.7 2446.47
   225.5 2445.19   235.3 2444.56   284.3 2442.46     304 2441.06   382.6 2437.06
   461.3 2433.54   464.2 2433.72   471.1 2434.15   476.2 2435.33   500.6 2442.34
   520.3 2445.68     540 2450.36     599 2459.82   608.8 2461.11   618.7 2461.47
   766.2 2458.79   795.7 2457.78   844.9 2454.28   864.6 2451.68   923.6 2445.86
#Mann= 3 , 0 , 0
       0     .06       0   464.2    .045       0   476.2     .06       0
Bank Sta=464.2,476.2
XS Rating Curve= 0 ,0
Exp/Cntr=0.3,0.1

Type RM Length L Ch R = 1 ,1289.9  ,381.4,399.2,411.2
XS GIS Cut Line= 3
     1918358.179      122831.275     1917921.393      122692.941
     1917530.824      122601.873
#Sta/Elev= 30
       0 2494.95    49.8 2492.01    59.8 2490.62    69.7 2485.58    79.7 2481.72
    99.6 2475.27   139.4 2460.56   149.4 2457.68   159.4 2455.92     239 2450.47
   338.6 2439.37   448.2 2432.06     450 2432.09   458.2 2432.23     462 2433.25
     468 2434.85   487.5 2446.33   497.3 2453.51   507.1 2459.57   526.6 2467.33
   536.4  2469.4   546.2 2469.99   585.3 2469.96   624.5 2472.52   653.8 2472.54
   663.6 2472.03   741.8  2462.7   790.7 2461.44   829.9    2459   859.2    2454
#Mann= 3 , 0 , 0
       0      .1       0     450    .045       0     462      .1       0
Bank Sta=450,462
XS Rating Curve= 0 ,0
Exp/Cntr=0.3,0.1

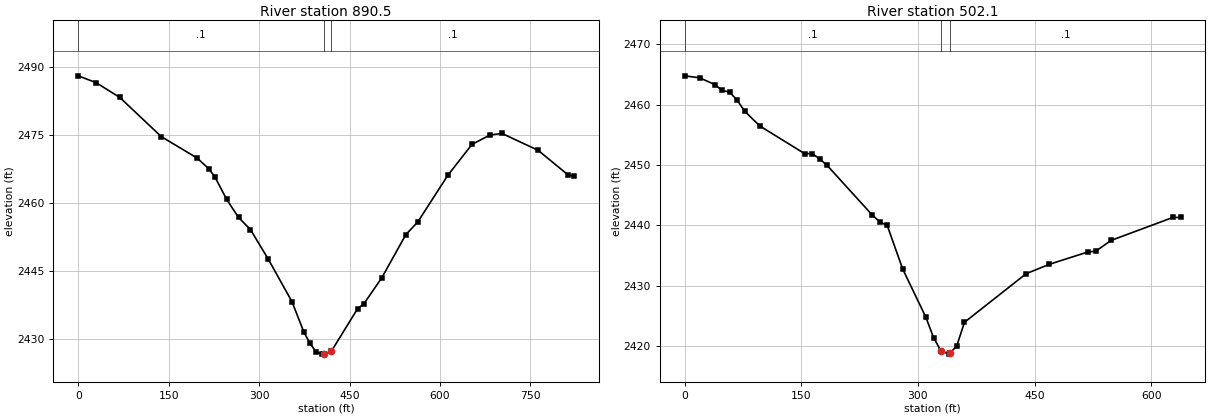
Type RM Length L Ch R = 1 ,890.5   ,399.6,388.3,378.4
XS GIS Cut Line= 3
     1918436.607       122733.23     1918183.464      122406.081
     1917911.356      122100.883
#Sta/Elev= 30
       0 2488.04    29.6 2486.54    68.9 2483.29   137.9 2474.64     197 2469.96
   216.7 2467.57   226.5 2465.83   246.2 2460.83   265.9 2456.86   285.6  2454.2
   315.2 2447.68   354.6  2438.3   374.3  2431.6   384.1 2429.23     394 2427.32
   403.8 2426.77   407.7 2426.79   419.7 2427.38   463.5  2436.8   473.5  2437.8
   503.4 2443.56   543.3 2453.07   563.2 2455.88   613.1 2466.16     653 2472.94
   682.9 2475.01   702.9 2475.35   762.7 2471.64   812.6 2466.21   822.5 2465.91
#Mann= 3 , 0 , 0
       0      .1       0   407.7    .045       0   419.7      .1       0
Bank Sta=407.7,419.7
XS Rating Curve= 0 ,0
Exp/Cntr=0.3,0.1

Type RM Length L Ch R = 1 ,502.1   ,501.3,501.9,502.6
XS GIS Cut Line= 3
     1918508.259      122369.323     1918451.523      122115.062
       1918100.6      121976.373
#Sta/Elev= 30
       0 2464.75    19.3 2464.42    38.6 2463.31    48.2 2462.34    57.9 2462.04
    67.5 2460.72    77.2 2458.89    96.5 2456.46   154.4 2451.86     164 2451.88
   173.7 2450.98   183.3 2449.91   241.2 2441.71   250.9 2440.57   260.5 2439.98
   280.4 2432.76   310.2 2424.78   320.1  2421.4   329.5 2419.22     340 2418.68
   341.5 2418.89   349.9 2420.04   359.8 2423.95   439.2    2432     469 2433.55
   518.7  2435.6   528.6 2435.72   548.5 2437.51   627.9 2441.31   637.8  2441.3
#Mann= 3 , 0 , 0
       0      .1       0   329.5    .045       0   341.5      .1       0
Bank Sta=329.5,341.5
XS Rating Curve= 0 ,0
Exp/Cntr=0.3,0.1

Chan Stop Cuts=-1
Use User Specified Reach Order=0
Composite Channel Slope=5